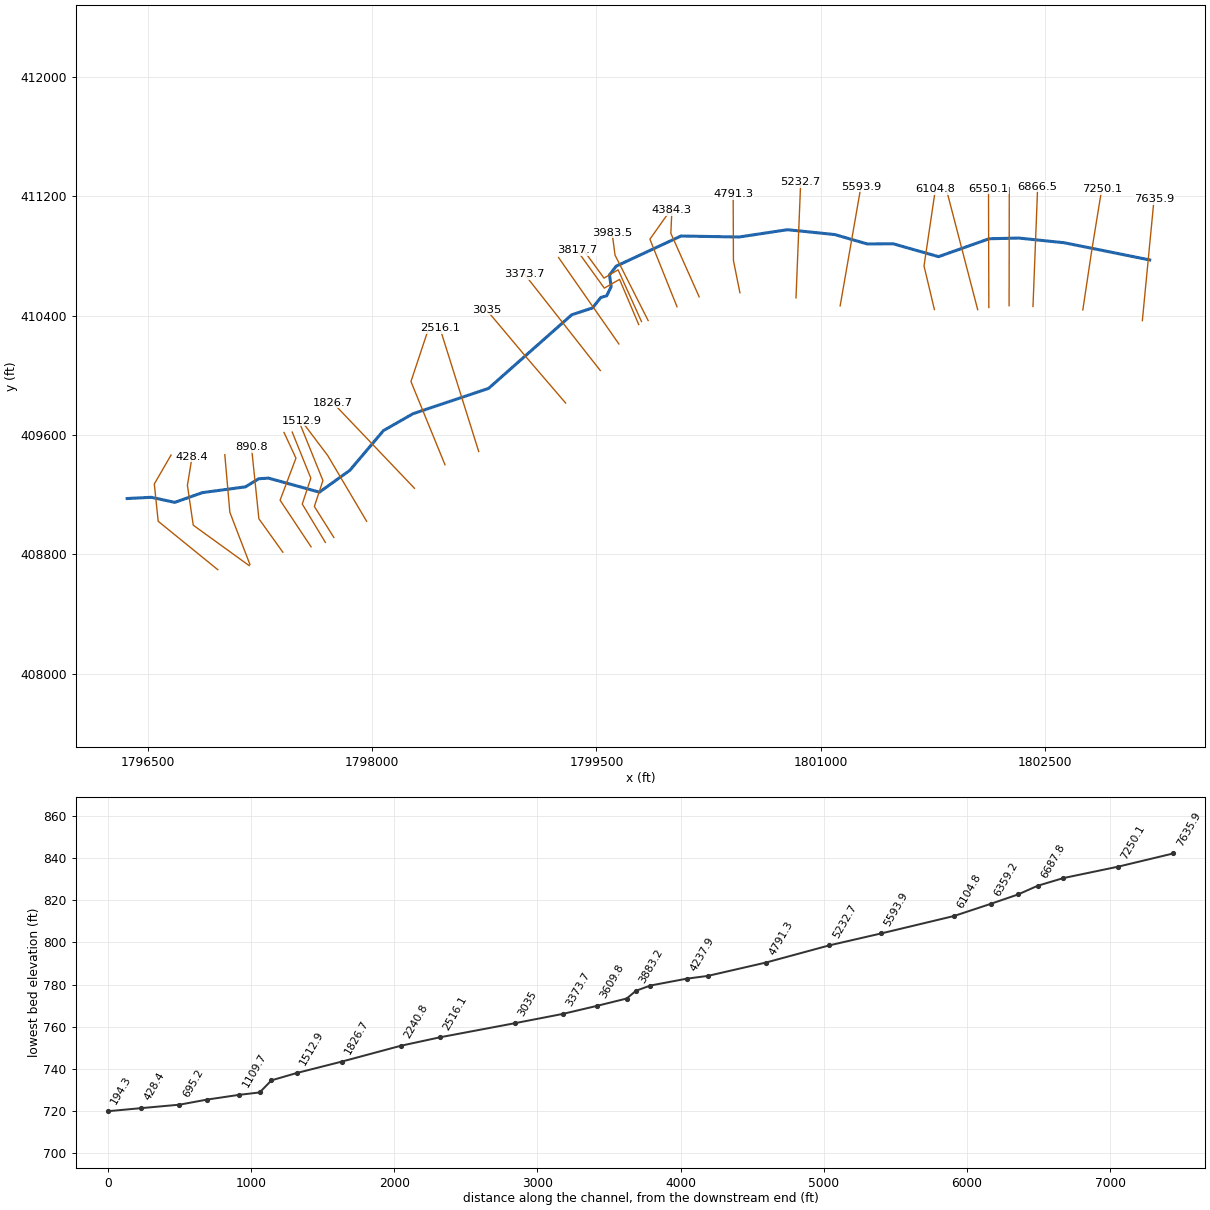
--- LFJOESCK.prj (project) ---

Proj Title=LFJOESCK
Current Plan=p01
Default Exp/Contr=0,0
English Units
Geom File=g01
Flow File=f01
Plan File=p01
BEGIN DESCRIPTION:
END DESCRIPTION:
DSS Export Rating Curves= 0
DSS Export Rating Curve Sorted= 0
DSS Export Volume Flow Curves= 0
DXF OffsetX= 0
DXF OffsetY= 0
DXF ScaleX= 0
DXF ScaleY= 0

--- LFJOESCK.p01 (plan) ---

Plan Title=Floodplain
Program Version=4.00
Geom File=g01
Flow File=f01
K Sum by GR=0
Std Step Tol=0.01
Critical Tol=0.01
Num of Std Step Trials=20
Max Error Tol=0.3
Flow Tol Ratio=0.001
Split Flow NTrial=30
Split Flow Tol=0.02
Split Flow Ratio=0.02
Log Output Level=0
Friction Slope Method=1
Unsteady Friction Slope Method=2
Unsteady Bridges Friction Slope Method=1
Global Log Level=0
CheckData=False
Run HTab=0
Run UNet=0
Run PostProcess=0
UNET Theta=0
UNET Theta Warmup=0
UNET ZTol=0
UNET ZSATol=0
UNET MxIter=0
UNET MaxInSteps=0
UNET DtIC=0
UNET DtMin=0
UNET MaxCRTS=0
UNET WFStab=0
UNET SFStab=0
UNET WFX=0
UNET SFX=0
UNET DSS MLevel=0
UNET DZMax Abort=0
UNET Convert EG Bridges=0
UNET Use Existing IB Tables=0
UNET Froude Limit=0
UNET Froude Power=0
Write IC File=0
Echo Input=False
Echo Output=False
Write Detailed=0

--- LFJOESCK.f01 (steady flow) ---

Flow Title=NFF Regression Equation
Program Version=4.00
Number of Profiles=1
Profile Names=P100yr
River Rch & RM=LFJOESCK,Main      ,7635.9
1155.000
River Rch & RM=LFJOESCK,Main      ,4791.3
1266.927
River Rch & RM=LFJOESCK,Main      ,3983.5
1637.384
River Rch & RM=LFJOESCK,Main      ,428.4
1704.508
Boundary for River Rch & Prof#=LFJOESCK,Main      ,1
Up Type=0
Dn Type=3
Dn Slope=0.008328

--- LFJOESCK.g01 (geometry) ---

Geom Title=USGS 10m DEM
Program Version=4.10

River Reach=LFJOESCK        ,Main
Reach XY= 30
1803198.91035295410772.5098238441802626.71858394410887.864908099
1802324.19819161410919.1863677651802125.57358885410914.602715507
1801787.14808461410794.6639790091801483.09915203410880.989593759
1801310.57587501410879.6828378441801093.56220144410942.616767094
1800776.72195587 410975.168867351800454.45619619 410926.34088102
1800064.91629285 410932.851038591799631.86663401410731.041074768
1799587.23647395410672.734432846 1799598.0343526410593.551848426
1799568.16105276410532.0060397681799529.28973943 410521.20848918
1799473.72259337410451.2243771851799334.66020745410405.130637348
1798778.36702868409911.7494062631798273.50583369409742.304863259
1798075.58890671409629.110535845 1797850.5890286409362.444074422
1797647.42801762409216.8564390991797306.76990628409310.707629353
1797241.49182162 409306.541299091797153.29744419409252.374412686
1796865.10313869409213.4857109341796680.38073909409148.207626268
1796524.13072354 409182.235445351796361.98406619409173.972338513

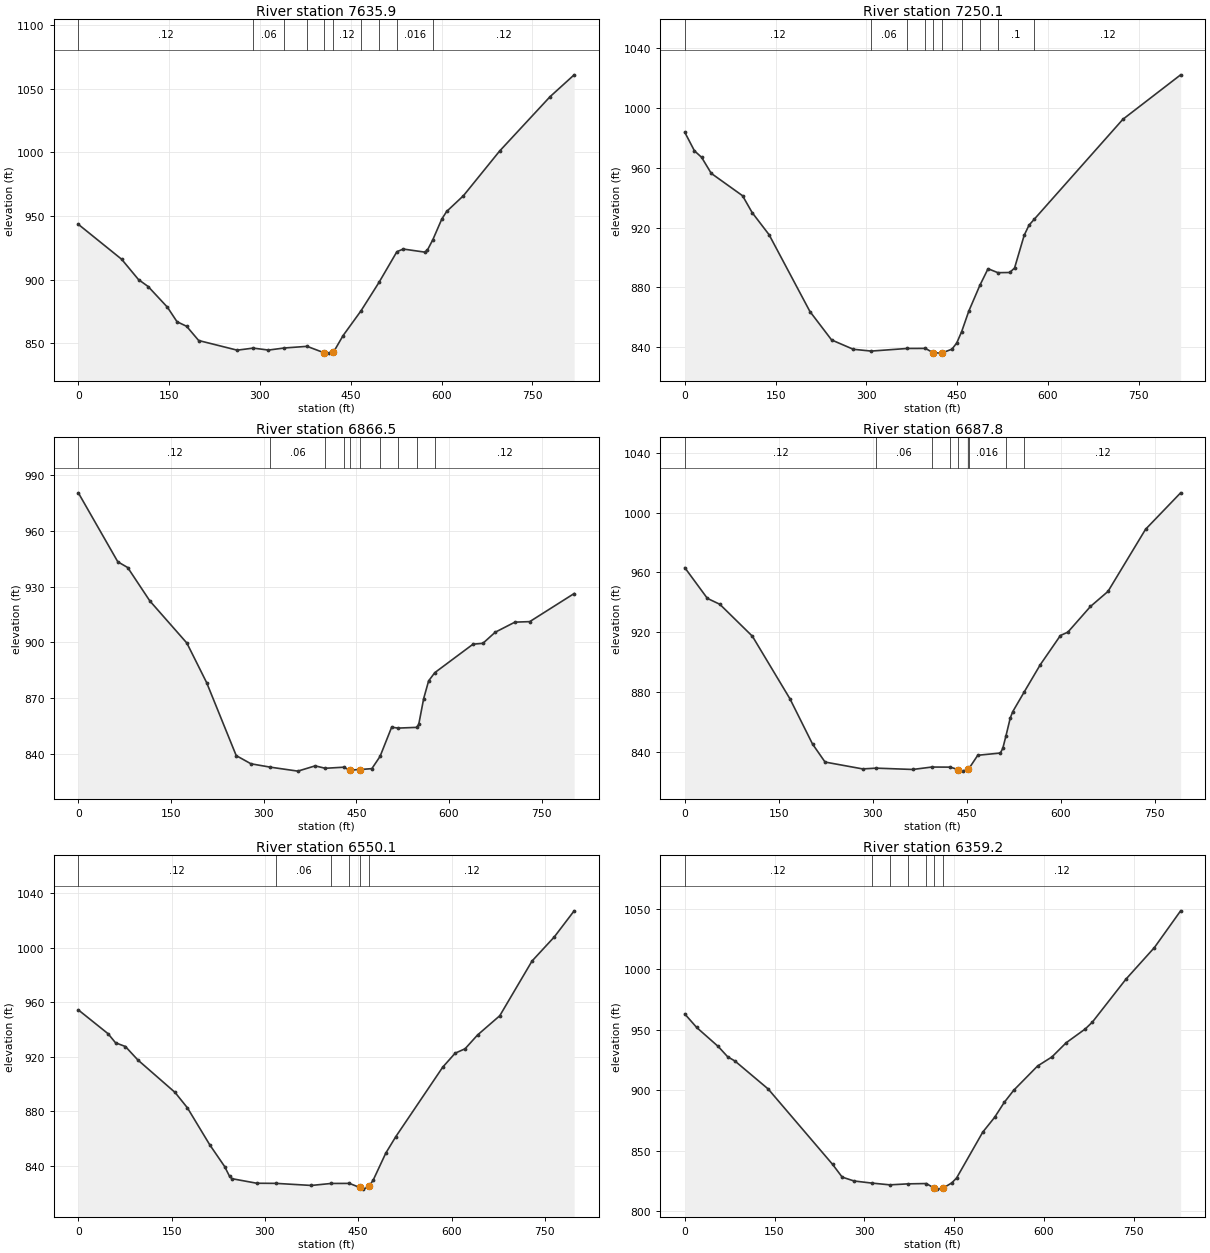
Type RM Length L Ch R = 1 ,7635.9  ,386.8,385.8,384.2
XS GIS Cut Line= 3
     1803149.764      410365.847     1803188.956      410773.467
     1803228.149      411181.087
#Sta/Elev= 30
       0  943.44    71.6     916    99.4  900.07   115.3  894.64   147.1  878.42
     163  867.01   178.9   863.4   198.8  852.24   262.4  844.67  288.83846.2903
   314.1  844.76  340.51846.3958  377.85847.6793   405.5   842.7   413.5  842.35
   421.4  843.08   437.3  856.11  466.87875.5261  496.54897.7936  526.21921.9587
   536.7  924.04   572.5  921.61   576.5  923.13  585.56931.3644   600.3  947.51
   608.3  953.51   636.1   965.9   695.8 1000.92   779.2 1043.63     819 1060.78
#Mann= 10 ,-1 , 0
       0     .12       0  288.83     .06       0  340.51     .05       0
  377.85    .016       0   405.5    .045       0   421.4     .12       0
  466.87      .1       0  496.54     .12       0  526.21    .016       0
  585.56     .12       0
Bank Sta=405.5,421.4
XS Rating Curve= 0 ,0
Exp/Cntr=0.3,0.1

Type RM Length L Ch R = 1 ,7250.1  ,381.1,383.6,386.6
XS GIS Cut Line= 3
     1802751.709      410437.435     1802812.454      410842.397
     1802878.197      411246.624
#Sta/Elev= 30
       0  983.68    15.9  971.33    27.8  966.94    43.7  956.24    95.4  941.29
   111.3  929.99   139.2  915.24   206.7  863.87   242.5  844.86   278.3  838.62
  307.94837.4172  367.67839.1719  397.54839.2093   409.5  836.44   421.4  836.05
   425.4  836.25   441.3  838.72   449.2  842.85  457.36850.4744   469.1  864.13
  487.29881.2943   500.9  892.48  517.21889.8372   536.7  889.96   544.7  892.95
   560.6  914.84   568.5  921.56  577.06925.4868   723.6  992.38     819 1022.12
#Mann= 10 ,-1 , 0
       0     .12       0  307.94     .06       0  367.67    .016       0
  397.54     .12       0   409.5    .045       0   425.4     .12       0
  457.36      .1       0  487.29    .016       0  517.21      .1       0
  577.06     .12       0
Bank Sta=409.5,425.4
XS Rating Curve= 0 ,0
Exp/Cntr=0.3,0.1

Type RM Length L Ch R = 1 ,6866.5  ,177.6,178.7,179.2
XS GIS Cut Line= 2
     1802418.548      410460.651     1802449.798      411262.734
#Sta/Elev= 30
       0  980.56    63.9   943.4    79.9  940.31   115.8   922.3   175.7  899.62
   207.7  878.31   255.6  838.98   279.5  834.56  311.09832.7316   355.4  830.61
   383.4  833.44  399.77832.1462  429.32832.7177   439.3   831.2   455.3  831.45
   475.2  831.96  488.44838.5158   507.2  854.26     518 853.802  547.56854.1816
   551.1  855.81   559.1  869.73   567.1  879.24  577.12883.6765     639  899.01
   654.9  899.46   674.9  905.45   706.8  910.89   730.8  911.16   802.7   926.3
#Mann= 10 ,-1 , 0
       0     .12       0  311.09     .06       0  399.77    .016       0
  429.32     .12       0   439.3    .045       0   455.3     .12       0
  488.44      .1       0     518    .016       0  547.56      .1       0
  577.12     .12       0
Bank Sta=439.3,455.3
XS Rating Curve= 0 ,0
Exp/Cntr=0.3,0.1

Type RM Length L Ch R = 1 ,6687.8  ,137.7,137.7,137.6
XS GIS Cut Line= 2
     1802258.825      410465.859     1802260.041      411257.005
#Sta/Elev= 30
       0  963.21      36  942.65    55.9  938.69   107.9  917.28   167.8  875.39
   203.8  845.12   223.8  833.04   283.7  828.45  305.65828.9565   363.6  828.07
  394.26829.6945  423.79829.6342   436.2  827.97   443.5  826.96   451.2  828.11
  453.33828.6458   467.5  837.58   503.5  839.07   507.4  842.15   512.4850.4326
   519.4  862.61   523.4  866.86  541.94880.2196   567.4  898.33   599.4  917.78
   611.3  920.04   647.3  937.21   675.3  947.31   735.2  988.89   791.2 1013.33
#Mann= 9 ,-1 , 0
       0     .12       0  305.65     .06       0  394.26    .016       0
  423.79     .12       0   436.2    .045       0   451.2     .12       0
  453.33    .016       0   512.4      .1       0  541.94     .12       0
Bank Sta=436.2,451.2
XS Rating Curve= 0 ,0
Exp/Cntr=0.3,0.1

Type RM Length L Ch R = 1 ,6550.1  ,184.8,190.9,196.5
XS GIS Cut Line= 2
     1802123.409      410453.706     1802121.152      411250.929
#Sta/Elev= 30
       0  954.26    47.8   936.8    59.8  930.15    75.7   927.4    95.7  917.54
   155.5  893.74   175.4  882.42   211.3  855.32   235.2   839.4   243.2  832.16
   247.1  830.46     287  827.12   317.8827.0355   374.7  825.51  406.41826.9677
  435.95 827.011   452.4  824.02   458.4  822.81   467.4  824.75   474.4  829.73
   494.3  849.19   510.2  861.14     586  912.34   605.9  922.52   621.8  925.74
   641.8  935.83   677.6  949.98   729.5  990.12   765.3  1007.8   797.2 1026.92
#Mann= 6 ,-1 , 0
       0     .12       0   317.8     .06       0  406.41    .016       0
  435.95     .05       0   452.4    .045       0   467.4     .12       0
Bank Sta=452.4,467.4
XS Rating Curve= 0 ,0
Exp/Cntr=0.3,0.1

Type RM Length L Ch R = 1 ,6359.2  ,263.4,254.5,245.1
XS GIS Cut Line= 2
     1802048.756      410439.817     1801840.423      411241.901
#Sta/Elev= 30
       0  962.99    19.9  951.83    55.8  936.18    71.7  927.62    83.7  924.19
   139.4  901.03     247  838.78     263  828.28   282.9  825.06  312.18823.3503
   342.7821.8737  373.21822.6935  403.73822.9565   417.1  819.07   422.3  818.34
   432.1  819.31   446.2  823.49   454.2  827.49     498  865.42   517.9  877.69
   533.9  889.98   549.8  900.02   589.6  920.02   613.6  927.52   637.5  939.26
   669.3  950.62   681.3  956.34   737.1  991.62   784.9 1017.87   828.7 1048.18
#Mann= 7 ,-1 , 0
       0     .12       0  312.18     .06       0   342.7     .05       0
  373.21    .016       0  403.73     .12       0   417.1    .045       0
   432.1     .12       0
Bank Sta=417.1,432.1
XS Rating Curve= 0 ,0
Exp/Cntr=0.3,0.1

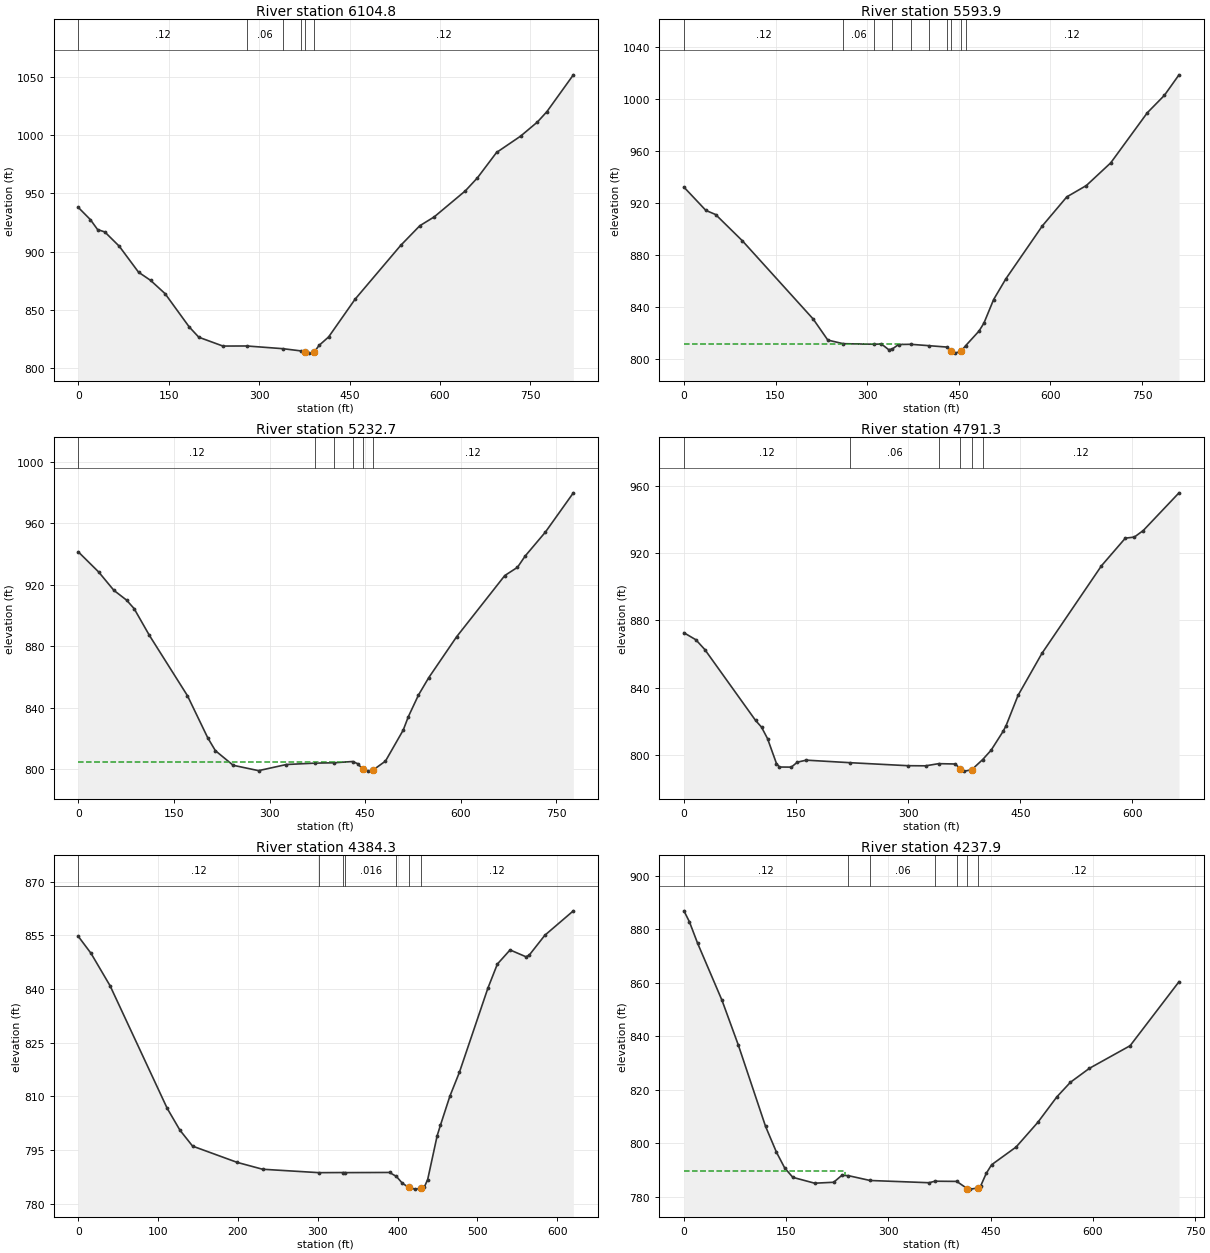
Type RM Length L Ch R = 1 ,6104.8  ,511.5,510.9,510.4
XS GIS Cut Line= 3
     1801759.426      410440.476     1801689.981      410732.142
      1801766.37      411247.767
#Sta/Elev= 30
       0  937.96      20  927.48      32  918.91      44  916.84      68  904.54
    99.9  882.24   119.9  875.19   143.9  863.79   183.9  835.19   199.9  826.27
   239.9  818.68  279.56818.7504  339.61816.4101  369.48814.5006   375.4  813.62
   383.4   812.6   391.3  813.49   399.3  819.24   415.2  826.53     459  858.95
   534.6  905.22   566.4  922.19   590.3  929.81     642  952.24   661.9  963.36
   693.7  985.23   733.5  999.25   761.4 1011.39   777.3 1020.41   821.1 1052.03
#Mann= 6 ,-1 , 0
       0     .12       0  279.56     .06       0  339.61    .016       0
  369.48     .12       0   375.4    .045       0   391.3     .12       0
Bank Sta=375.4,391.3
XS Rating Curve= 0 ,0
Exp/Cntr=0.3,0.1

Type RM Length L Ch R = 1 ,5593.9  ,358.3,361.2,364.1
XS GIS Cut Line= 2
     1801129.217      410464.781     1801268.106      411263.392
#Sta/Elev= 30
       0  932.14    35.9  914.21    51.9  911.02    95.8  890.75   211.6  830.55
   235.6  814.32  260.73811.5389  311.34811.1272   323.4   811.3   335.4  806.88
  341.32807.5004   351.4  810.91   371.3811.0703  401.28810.0005  431.25808.9198
  437.45  805.56   443.2  804.27  453.27  805.59  461.24809.9859   483.2   821.3
   491.2  827.39   507.1  845.57   527.1   861.5     587  902.38   626.9  924.62
   658.9  933.36   698.8  950.82   758.7  989.41   786.6 1002.79   810.6 1018.63
#Mann= 10 ,-1 , 0
       0     .12       0  260.73     .06       0  311.34     .12       0
  341.32     .08       0   371.3     .06       0  401.28    .016       0
  431.25      .1       0  437.45    .045       0  453.27      .1       0
  461.24     .12       0
#XS Ineff= 2 , 0
       0   359.4   811.1               0
Permanent Ineff=
       F       F
Bank Sta=437.45,453.27
XS Rating Curve= 0 ,0
Exp/Cntr=0.3,0.1

Type RM Length L Ch R = 1 ,5232.7  ,440.3,441.3,442.3
XS GIS Cut Line= 2
     1800834.079      410518.601     1800865.329      411294.642
#Sta/Elev= 30
       0   941.3    31.9  928.23    55.8  916.27    75.7   909.9    87.6  904.36
   111.5  886.98   171.3  847.66   203.1  820.29   215.1  811.91     243  802.41
   282.8  798.92   326.6  802.92  371.36 803.812  400.92804.0397  430.48804.8677
   438.1  803.49   446.1     800     454  798.61     462  799.18   481.9  805.13
   509.8  825.35   517.8  834.04   533.7  848.13   549.6   859.3   593.5  886.02
   669.1  925.88     689  931.23     701  938.53   732.9   954.2   776.7  979.71
#Mann= 6 ,-1 , 0
       0     .12       0  371.36      .1       0  400.92    .016       0
  430.48      .1       0   446.1    .045       0     462     .12       0
#XS Ineff= 2 , 0
       0   422.2  804.83               0
Permanent Ineff=
       F       F
Bank Sta=446.1,462
XS Rating Curve= 0 ,0
Exp/Cntr=0.3,0.1

Type RM Length L Ch R = 1 ,4791.3  ,397.6,407.1,416.4
XS GIS Cut Line= 3
     1800459.079      410553.323     1800415.676      410768.601
      1800413.94      411211.309
#Sta/Elev= 30
       0  872.66      16   868.5      28  862.66    95.8   820.6   103.8  816.59
   111.8  809.82   123.8  794.97   127.8   792.9   143.7  792.84   151.7  795.78
   163.7  796.98  222.53795.4653   299.4  793.69   323.3  793.61  340.67794.8932
   363.2   794.7   369.9  791.66   375.2  790.46   384.9  791.25  399.75797.3681
     411  802.93     427   814.1     431  817.52     447  835.48   478.9   860.4
   558.6  912.47   590.5  928.88   602.5   929.5   614.5  933.41   662.3   955.8
#Mann= 6 ,-1 , 0
       0     .12       0  222.53     .06       0  340.67    .016       0
   369.9    .045       0   384.9      .1       0  399.75     .12       0
#XS Ineff= 2 , 0
       0     267                       0
Permanent Ineff=
       F       F
Bank Sta=369.9,384.9
XS Rating Curve= 0 ,0
Exp/Cntr=0.3,0.1

Type RM Length L Ch R = 1 ,4384.3  ,147.3,146.4,145.5
XS GIS Cut Line= 3
     1800186.509      410525.545     1799997.273      410950.892
     1800004.217      411105.406
#Sta/Elev= 30
       0  854.74    15.9  850.01    39.8  840.94   111.4  806.66   127.3  800.58
   143.2  796.11     199  791.57   230.8  789.65  301.55788.6921   332.1788.7269
  333.88788.7041   389.9  788.75  398.53787.6331   405.9  785.75   413.8  784.59
   421.8  784.09   429.7  784.28   433.7  784.77   437.7  786.78   449.6  799.04
   453.6   801.9   465.5  810.07   477.4  816.73   513.1  840.25     525     847
   540.9  850.95   560.7  849.05   564.7  849.44   584.5  855.06   620.2  861.88
#Mann= 7 ,-1 , 0
       0     .12       0  301.55    .016       0   332.1     .06       0
  333.88    .016       0  398.53     .12       0   413.8    .045       0
   429.7     .12       0
Bank Sta=413.8,429.7
XS Rating Curve= 0 ,0
Exp/Cntr=0.3,0.1

Type RM Length L Ch R = 1 ,4237.9  ,252.2,254.3,256.4
XS GIS Cut Line= 3
     1800038.506      410458.965     1799857.299      410911.439
     1799995.103      411106.752
#Sta/Elev= 30
       0  886.98       8   882.9      20  874.88    55.9  853.44    79.9  836.66
   119.8  806.25   135.8  796.58   147.8  790.73   159.8  787.19   191.8     785
   219.7  785.35   231.7  787.94  241.24787.8267  273.06786.0172   359.6  785.18
  368.51785.7464  400.33785.6702   415.5     783   419.5  782.78   431.5  783.17
   435.5  784.02   443.5  788.64   451.4   791.9   487.4  798.55   519.3   807.8
   547.2  817.33   567.1  822.79     595  828.02   654.7  836.48   726.4  860.44
#Mann= 7 ,-1 , 0
       0     .12       0  241.24    .016       0  273.06     .06       0
  368.51    .016       0  400.33     .12       0   415.5    .045       0
   431.5     .12       0
#XS Ineff= 2 , 0
          236.12  789.53
Permanent Ineff=
       F       F
Bank Sta=415.5,431.5
XS Rating Curve= 0 ,0
Exp/Cntr=0.3,0.1

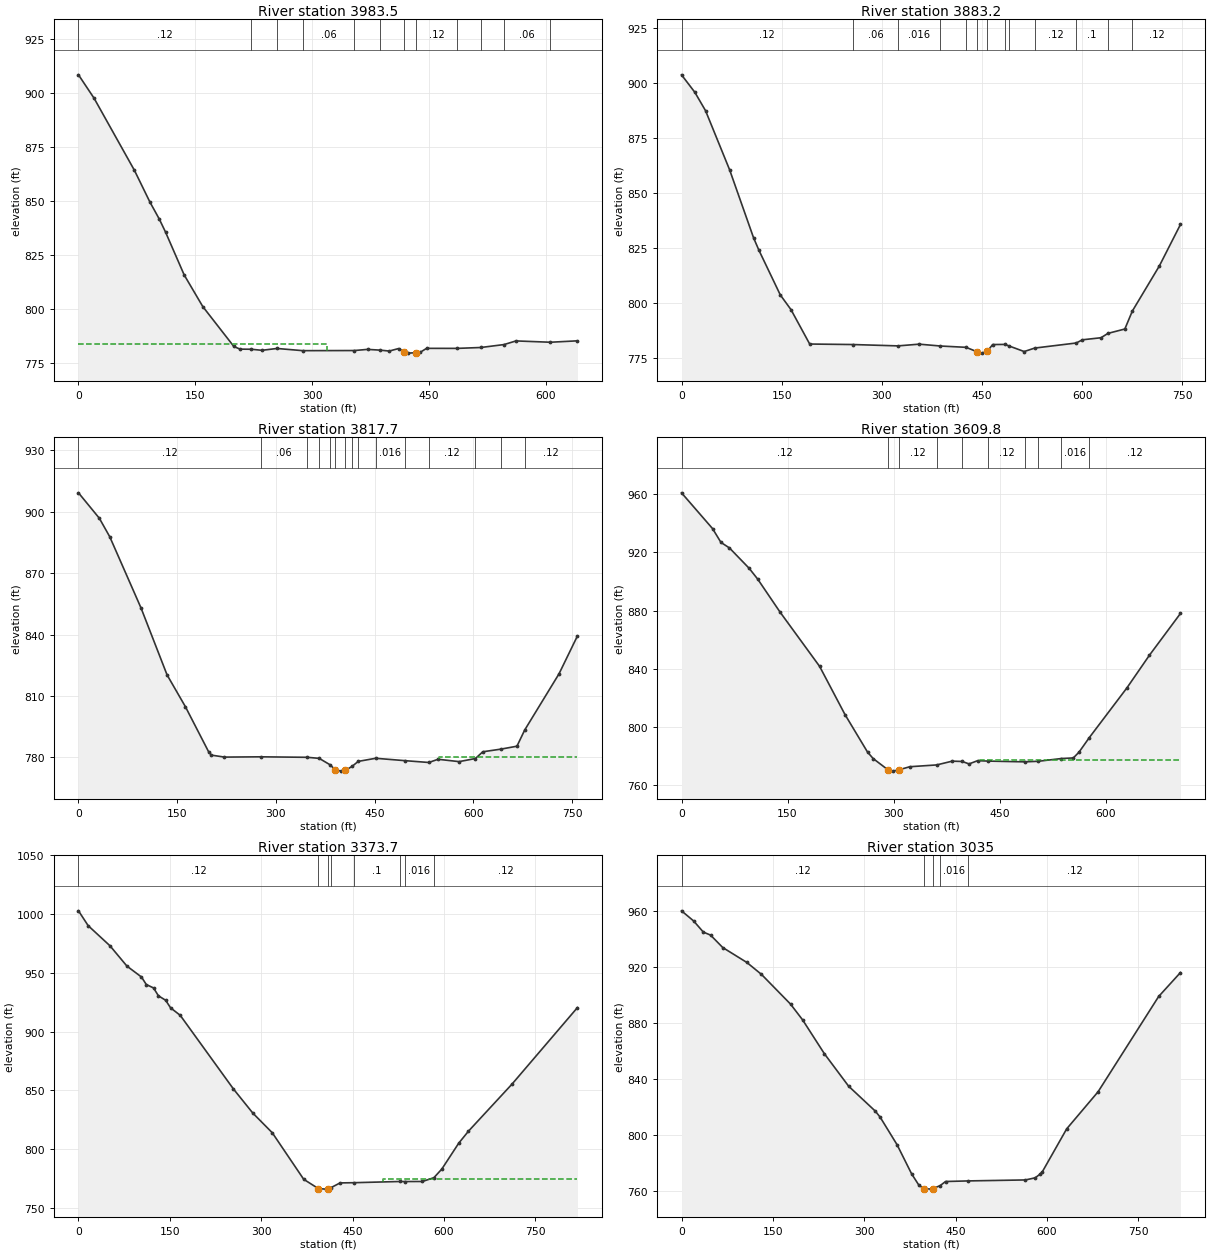
Type RM Length L Ch R = 1 ,3983.5  ,35.1,100.4,139.3
XS GIS Cut Line= 3
     1799845.407      410366.662     1799624.053       410805.03
     1799604.521      410953.684
#Sta/Elev= 30
       0  908.26      20  897.45    71.9  864.05    91.8  849.37   103.8  841.53
   111.8  835.53   135.8  815.67   159.7  801.04   199.6  782.58   207.6  781.35
  221.93781.3093   235.6  780.81  255.02781.6636  288.11780.6495  354.29780.7086
   371.3  781.24  387.38780.8988   399.3  780.47   411.2  781.63   418.8  779.93
   423.2  779.51   433.8  779.71   439.2  779.94   447.2  781.72  486.64781.7077
  516.87782.1153  546.66783.4687   562.1  785.16  606.24784.5472     641   785.2
#Mann= 12 ,-1 , 0
       0     .12       0  221.93     .06       0  255.02     .12       0
  288.11     .06       0  354.29    .016       0  387.38     .12       0
   418.8    .045       0   433.8     .12       0  486.64     .06       0
  516.87    .016       0  546.66     .06       0  606.24      .1       0
#XS Ineff= 2 , 0
           319.3  783.78
Permanent Ineff=
       F       F
Bank Sta=418.8,433.8
XS Rating Curve= 0 ,0
Exp/Cntr=0.3,0.1

Type RM Length L Ch R = 1 ,3883.2  ,92.8,65.4,63.5
XS GIS Cut Line= 4
     1799800.919      410360.151     1799644.669      410706.289
     1799550.268       410650.95     1799398.358      410859.283
#Sta/Elev= 30
       0  903.66      20  895.69      36  887.33      72  860.45   107.9  829.48
   115.9  823.83   147.9  803.51   163.9  796.82   191.9  781.17  256.91780.9372
  324.17780.3246   355.8  781.11  387.49780.2706  425.98779.6688   442.3  777.68
   450.1  777.03   457.9  777.91   465.8  780.93  484.38780.9949  490.66  780.26
     513  777.75  528.76779.3313  590.93781.6373   600.3   783.1     628  784.03
  638.42786.0129   663.7     788  674.98796.1859   715.3  816.65     747  835.58
#Mann= 13 ,-1 , 0
       0     .12       0  256.91     .06       0  324.17    .016       0
  387.49     .12       0  425.98     .06       0   442.3    .045       0
   457.9     .12       0  484.38    .016       0  490.66      .1       0
  528.76     .12       0  590.93      .1       0  638.42    .016       0
  674.98     .12       0
#XS Ineff= 2 , 0
       0     350             560       0
Permanent Ineff=
       F       F
Bank Sta=442.3,457.9
XS Rating Curve= 0 ,0
Exp/Cntr=0.3,0.1

Type RM Length L Ch R = 1 ,3817.7  ,242,208,174
XS GIS Cut Line= 4
     1799782.473      410339.535     1799654.434       410642.27
     1799552.438      410583.676     1799370.146      410836.497
#Sta/Elev= 30
       0  909.24    31.7  896.81    47.5  887.78      95  853.01   134.6   820.3
   162.4  804.81     198  782.59     202  781.14   221.8  780.18  276.62780.3174
  347.64780.0786  365.68779.5665   381.7776.5213   390.4  773.97   399.3  773.33
   405.4  773.66  415.76775.6857  424.98778.0899  451.52779.6039  495.85778.4467
  532.26777.5485   546.2  779.12   578.2  777.97  603.02 779.485   614.2  782.78
   641.5784.0615   666.1   785.5  677.92793.4297     730  820.84     758  839.35
#Mann= 15 ,-1 , 0
       0     .12       0  276.62     .06       0  347.64    .016       0
  365.68     .06       0   381.7     .12       0   390.4    .045       0
   405.4     .12       0  415.76    .016       0  424.98     .12       0
  451.52    .016       0  495.85      .1       0  532.26     .12       0
  603.02      .1       0   641.5    .016       0  677.92     .12       0
#XS Ineff= 2 , 0
                          547.83          780.07
Permanent Ineff=
       F       F
Bank Sta=390.4,405.4
XS Rating Curve= 0 ,0
Exp/Cntr=0.3,0.1

Type RM Length L Ch R = 1 ,3609.8  ,234.7,236.1,237.2
XS GIS Cut Line= 2
     1799649.827      410209.472     1799246.448      410788.754
#Sta/Elev= 30
       0  960.86    43.9  936.31    55.8  926.82    67.8  923.03    95.7  909.05
   107.7  901.69   139.6  878.86   195.4  841.71   231.3  808.64   263.2  782.88
   271.2  778.42   292.8  770.47   299.1  769.83   307.8  770.76     323  772.85
  360.98774.0836   382.9  776.67  396.97776.4708   406.8  774.79   418.8  776.98
  434.17776.7239  485.86776.1878  504.94776.5983  537.55778.4794   554.3  778.89
   562.3  782.81  576.93792.8452   630.1  826.94     662  849.39   705.9  878.06
#Mann= 10 ,-1 , 0
       0     .12       0   292.8    .045       0   307.8     .12       0
  360.98    .016       0  396.97      .1       0  434.17     .12       0
  485.86     .06       0  504.94      .1       0  537.55    .016       0
  576.93     .12       0
#XS Ineff= 2 , 0
                          422.67          777.38
Permanent Ineff=
       F       F
Bank Sta=292.8,307.8
XS Rating Curve= 0 ,0
Exp/Cntr=0.3,0.1

Type RM Length L Ch R = 1 ,3373.7  ,337.7,338.7,339.2
XS GIS Cut Line= 3
     1799525.535      410031.695     1799272.756      410353.864
     1799019.976      410676.033
#Sta/Elev= 30
       0  1002.9    15.9  990.26    51.7  973.14    79.5  955.87   103.4  946.57
   111.3  940.18   123.2  937.26   131.2  930.59   143.1  926.76   151.1  920.37
     167  913.96   254.4  851.24   286.2  830.73   318.1  814.01   369.7   774.4
   393.6  766.55   405.5  766.04   409.5  766.19  414.79767.3807   429.4  771.33
  452.33771.5159  527.41772.5374  535.52772.4979   564.6  772.55  583.37 775.765
   596.4  783.13   624.2  805.18   640.1  815.35   711.7  855.47     819  920.55
#Mann= 8 ,-1 , 0
       0     .12       0   393.6    .045       0   409.5     .12       0
  414.79    .016       0  452.33      .1       0  527.41     .05       0
  535.52    .016       0  583.37     .12       0
#XS Ineff= 2 , 0
                          499.83          774.26
Permanent Ineff=
       F       F
Bank Sta=393.6,409.5
XS Rating Curve= 0 ,0
Exp/Cntr=0.3,0.1

Type RM Length L Ch R = 1 ,3035    ,528,518.9,509.9
XS GIS Cut Line= 3
     1799293.909      409813.709     1799027.539      410124.729
       1798764.5      410438.614
#Sta/Elev= 30
       0   959.9    19.9  952.67    35.8  944.76    47.7  942.59    67.6  933.76
   107.3  923.09   131.2  914.61   178.9  893.45   198.8  882.16   234.6  858.01
   274.3  834.93     318   817.2     326  812.89   353.8  793.22   377.7  772.46
   389.6  764.39   397.5  761.98   409.5  761.57   412.5  761.86  424.74764.1314
   433.4     767  470.73767.4222   564.6  768.12   580.5  769.63   588.4   772.2
   592.4  774.05   632.2   804.5   683.8  830.97   783.2  898.86     819  915.93
#Mann= 5 ,-1 , 0
       0     .12       0   397.5    .045       0   412.5     .12       0
  424.74    .016       0  470.73     .12       0
#XS Ineff= 2 , 0
       0                  509.64       0
Permanent Ineff=
       F       F
Bank Sta=397.5,412.5
XS Rating Curve= 0 ,0
Exp/Cntr=0.3,0.1

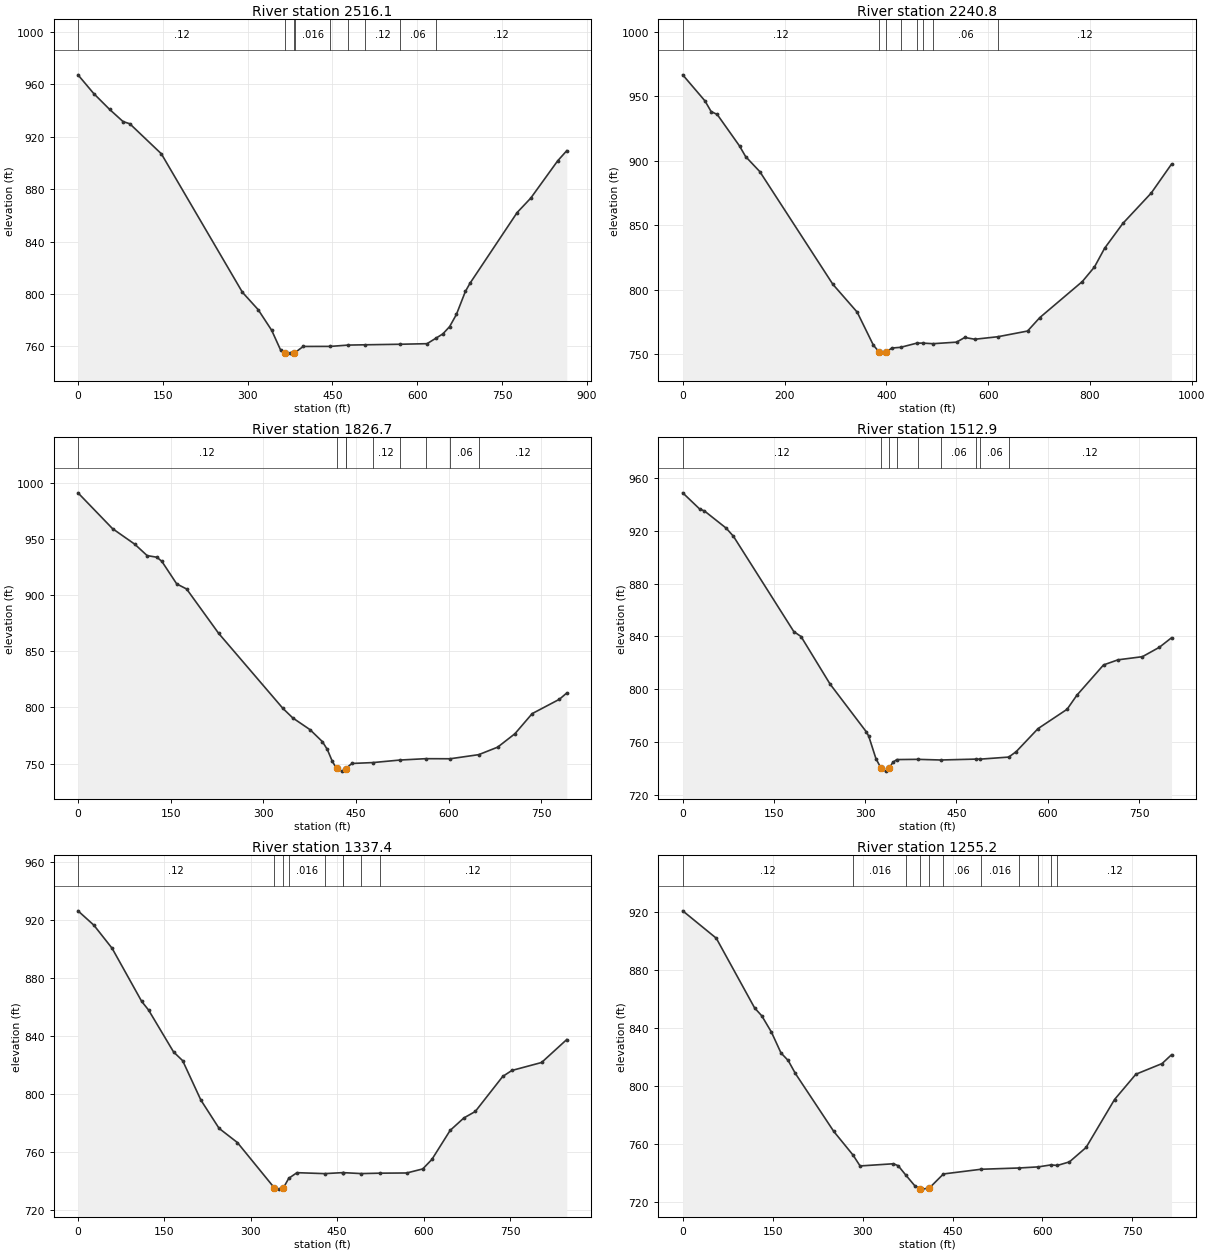
Type RM Length L Ch R = 1 ,2516.1  ,273.4,275.3,277.1
XS GIS Cut Line= 2
     1798712.724         409489.     1798454.044      410313.653
#Sta/Elev= 30
       0  967.31    27.9     953    55.8  940.98    79.7  931.64    91.6  929.97
   147.4  907.05   290.8  801.33   318.6   788.1   342.5  772.35   358.4  757.19
   366.3  755.17   374.4  754.92   381.3  754.98  384.54755.5771   398.3  760.02
  446.45760.0648  477.41761.0499  508.36761.2864  570.27 761.698   617.3  762.13
  632.19766.1143   645.2   769.6   657.2  775.18   669.1   784.4     685  801.97
     693  808.12   776.6  862.24   800.6  873.22   848.3  901.72   864.3  909.42
#Mann= 9 ,-1 , 0
       0     .12       0   366.3    .045       0   381.3     .12       0
  384.54    .016       0  446.45     .12       0  477.41     .06       0
  508.36     .12       0  570.27     .06       0  632.19     .12       0
Bank Sta=366.3,381.3
XS Rating Curve= 0 ,0
Exp/Cntr=0.3,0.1

Type RM Length L Ch R = 1 ,2240.8  ,405.4,414.1,422.6
XS GIS Cut Line= 3
      1798487.03      409400.458     1798259.599       409957.75
     1798372.447      410298.028
#Sta/Elev= 30
       0  966.51    43.8  946.27    55.8  938.07    67.8   935.8   111.6   911.4
   123.6  903.17   151.5  891.51     295  804.21   342.8  782.63   374.7  756.98
   385.4  752.04   394.6  750.87   400.4  751.66   410.6   754.8  428.12755.3681
  460.02 758.614   471.5758.6373  491.93758.1796   538.1  759.38   554.1  762.99
     574  761.63   619.1763.5695   677.6  767.99   701.5  778.36   785.2  806.35
     809  817.61     829  832.15   864.8  851.37   920.6  874.93   960.4  897.31
#Mann= 8 ,-1 , 0
       0     .12       0   385.4    .045       0   400.4    .016       0
  428.12     .12       0  460.02     .06       0   471.5     .12       0
  491.93     .06       0   619.1     .12       0
Bank Sta=385.4,400.4
XS Rating Curve= 0 ,0
Exp/Cntr=0.3,0.1

Type RM Length L Ch R = 1 ,1826.7  ,318.8,313.8,308.5
XS GIS Cut Line= 2
     1798283.364      409242.422     1797738.077      409815.409
#Sta/Elev= 30
       0  991.02    55.9  959.15    91.9  945.28   111.9  935.15   127.8  933.68
   135.8  929.96   159.8  909.94   175.8  905.42   227.7   865.9   331.6  799.15
   347.6  790.65   375.5  780.22   395.5  769.56   403.5  762.57   411.5  752.12
   418.4  745.68   427.4   743.3   433.4  745.54  434.29746.1407   443.4  750.12
  477.13750.9084  520.72753.1555  562.82754.3812  602.27754.3077  648.51757.9651
   679.1  764.62   707.1  776.59     735  794.48     779  807.24     791  812.85
#Mann= 9 ,-1 , 0
       0     .12       0   418.4    .045       0   433.4     .12       0
  434.29    .016       0  477.13     .12       0  520.72     .06       0
  562.82     .12       0  602.27     .06       0  648.51     .12       0
Bank Sta=418.4,433.4
XS Rating Curve= 0 ,0
Exp/Cntr=0.3,0.1

Type RM Length L Ch R = 1 ,1512.9  ,195.4,175.4,150.2
XS GIS Cut Line= 3
     1797963.303       409021.32     1797702.886      409462.293
     1797527.539      409694.932
#Sta/Elev= 30
       0  948.71    27.8  936.48    35.7  934.98    71.5  921.93    83.4  915.77
   182.6   843.6   194.5  839.84   242.2  803.84   301.7   767.7   305.7  764.43
   317.6  747.32   325.5  740.55   333.5  737.89   339.5  740.39   345.4  744.54
  351.83746.6389  386.13746.8232  424.03746.3211  482.11     747  489.04746.9752
  535.84748.5319     548  752.59     584  770.09   631.8  784.76   647.8  795.35
   691.7  818.34   715.6  822.22   755.6  824.59   783.5  831.72   803.4  838.91
#Mann= 9 ,-1 , 0
       0     .12       0   325.5    .045       0   339.5     .12       0
  351.83    .016       0  386.13     .12       0  424.03     .06       0
  482.11     .12       0  489.04     .06       0  535.84     .12       0
#XS Ineff= 2 , 0
       0                     389       0
Permanent Ineff=
       F       F
Bank Sta=325.5,339.5
XS Rating Curve= 0 ,0
Exp/Cntr=0.3,0.1

Type RM Length L Ch R = 1 ,1337.4  ,82.1,82.3,87.1
XS GIS Cut Line= 4
     1797743.974      408913.392     1797613.766      409120.858
     1797671.058      409294.469      1797513.65      409684.515
#Sta/Elev= 30
       0  926.23    27.6  916.34    59.3  900.37   110.6   863.8   122.5  857.87
   165.9  828.98   181.7  822.95   213.3  795.81   244.9  776.31   276.7  766.53
   340.3  735.54   348.3  734.42   356.2  735.04  365.84741.8798   380.1  745.76
  428.05 745.108  459.78745.7958   459.9 745.794  491.75745.1349   523.6 745.414
   570.6  745.55   598.4  748.34   614.3   754.9     646  774.91   669.8  783.47
   689.6  787.93   737.3  812.11   753.1   816.2   804.7   821.7   848.4  837.53
#Mann= 9 ,-1 , 0
       0     .12       0   340.3    .045       0   356.2     .12       0
  365.84    .016       0  428.05     .12       0  459.78    .016       0
   459.9     .12       0  491.75     .06       0   523.6     .12       0
Bank Sta=340.3,356.2
XS Rating Curve= 0 ,0
Exp/Cntr=0.3,0.1

Type RM Length L Ch R = 1 ,1255.2  ,146.5,145.4,144.6
XS GIS Cut Line= 4
     1797687.355       408880.04     1797532.841      409136.985
     1797590.132      409310.596     1797465.711      409619.045
#Sta/Elev= 30
       0  920.63      56  901.73   119.9  853.66   131.9  848.18   147.9  837.01
   163.9   822.6   175.9   817.4   187.9  808.44   251.8  768.55  284.13752.1247
   295.8  744.66   351.5  746.17   359.4   744.8  372.63 738.076   387.3  730.88
   396.2  728.96   399.2  728.67   411.2  729.39  434.84 739.134  497.39  742.37
  561.09743.2563  592.94744.0127  614.16745.3814  624.78745.0005     645  747.47
   672.7  757.39   720.2  790.48   755.8  807.93   799.4  815.26   815.2  821.35
#Mann= 11 ,-1 , 0
       0     .12       0  284.13    .016       0  372.63     .12       0
   396.2    .045       0   411.2     .12       0  434.84     .06       0
  497.39    .016       0  561.09     .06       0  592.94     .12       0
  614.16     .06       0  624.78     .12       0
Bank Sta=396.2,411.2
XS Rating Curve= 0 ,0
Exp/Cntr=0.3,0.1

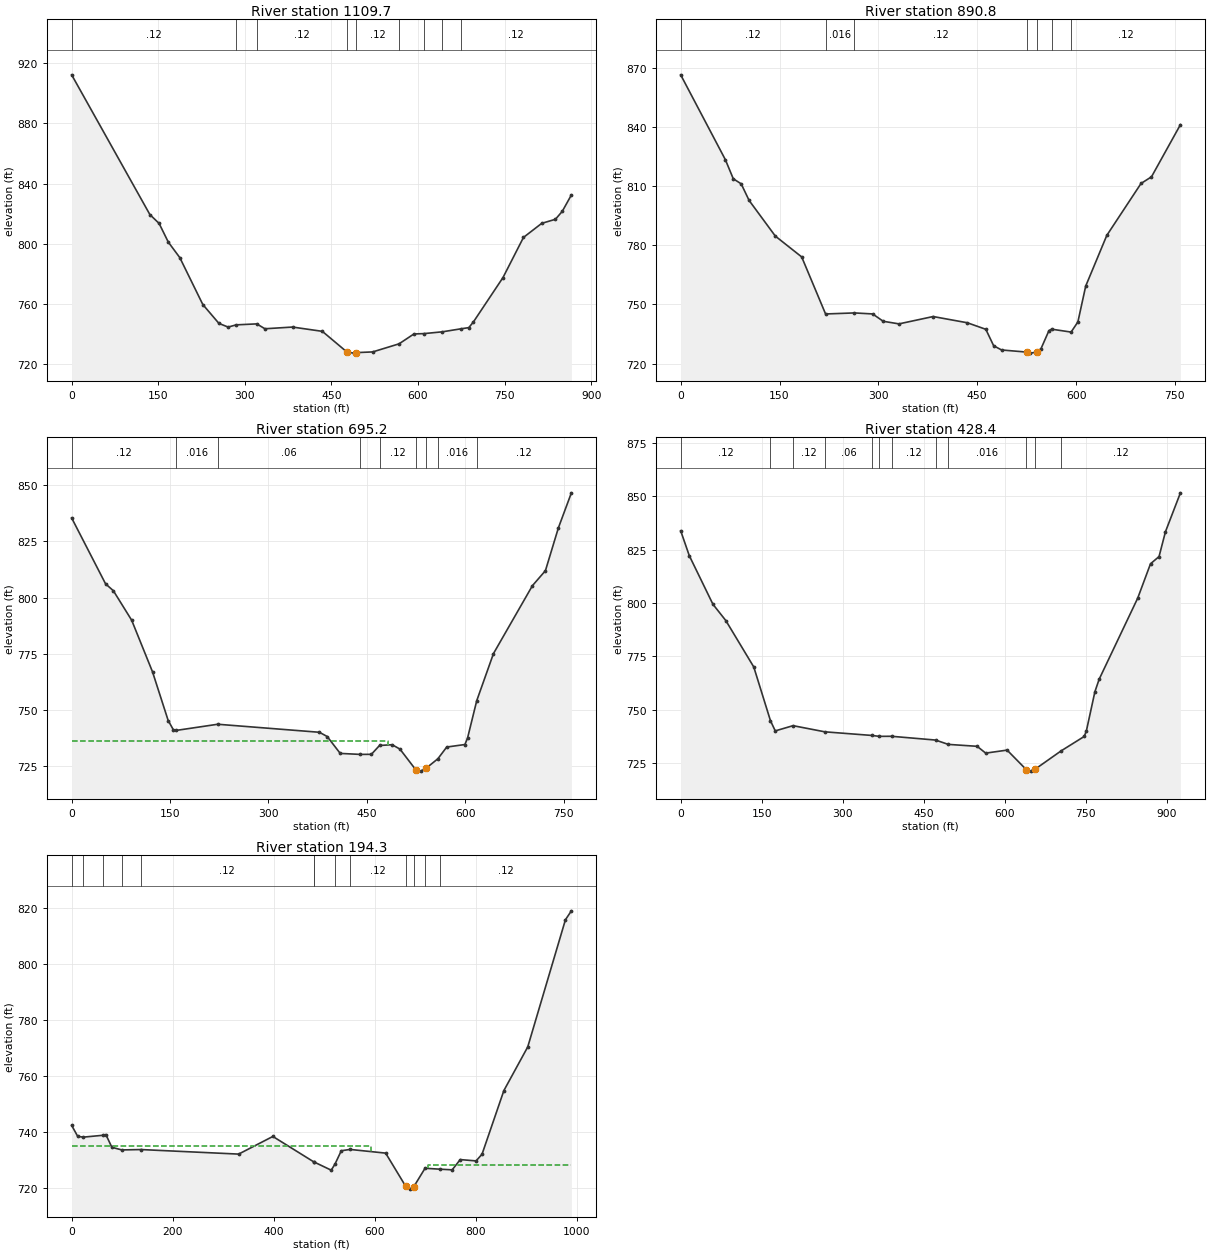
Type RM Length L Ch R = 1 ,1109.7  ,209,219,229.3
XS GIS Cut Line= 4
     1797591.703      408850.328     1797384.672      409162.611
     1797490.647      409444.715     1797410.786       409616.59
#Sta/Elev= 30
       0  912.08   135.5   819.4   151.5  813.52   167.4  801.14   187.3  790.87
   227.2  759.73   255.1  747.22     271  744.79  285.14746.2612  320.58746.9014
   334.8  743.67   382.6   744.8   434.2  741.96   477.5  728.04   489.7  727.51
   492.5  727.84   521.4  728.31  567.05733.6689   592.8  740.21  610.47740.4635
  642.02741.6432  673.58743.5942   687.9  744.42   695.8  748.15   747.1  777.62
   782.6  804.25   814.2  813.58   837.9  816.27   849.8  821.55   865.6  832.43
#Mann= 9 ,-1 , 0
       0     .12       0  285.14    .016       0  320.58     .12       0
   477.5    .045       0   492.5     .12       0  567.05     .06       0
  610.47    .016       0  642.02     .06       0  673.58     .12       0
Bank Sta=477.5,492.5
XS Rating Curve= 0 ,0
Exp/Cntr=0.3,0.1

Type RM Length L Ch R = 1 ,890.8   ,195.1,195.5,195.2
XS GIS Cut Line= 3
     1797402.988      408814.434     1797242.831      409038.392
     1797193.352      409518.861
#Sta/Elev= 30
       0  866.32    67.8  823.32    79.8  813.66    91.8  811.08   103.8  802.68
   143.6  784.61   183.6  774.05  219.85745.1446  263.68745.6702   291.3  745.16
   307.3  741.44   331.2  740.12   383.1  743.84     435  740.68     463  737.37
   474.9  729.04   486.9   726.9   525.4  725.82   530.8   725.3   540.4  725.85
   546.8   727.6   558.8   736.7  562.73737.4387  592.42735.9676   602.7  741.11
   614.6   759.3   646.6  784.97   698.5  811.26   714.4  814.65   758.3  841.07
#Mann= 7 ,-1 , 0
       0     .12       0  219.85    .016       0  263.68     .12       0
   525.4    .045       0   540.4     .12       0  562.73    .016       0
  592.42     .12       0
Bank Sta=525.4,540.4
XS Rating Curve= 0 ,0
Exp/Cntr=0.3,0.1

Type RM Length L Ch R = 1 ,695.2   ,265.5,266.8,268.1
XS GIS Cut Line= 3
     1797182.936      408732.403     1797048.821      409081.361
     1797014.967       409468.08
#Sta/Elev= 30
       0  835.46    51.7  806.16    63.6  803.08    91.5  789.98   123.3  767.01
   147.2  745.34   155.1  741.23  159.44740.9555  222.73743.6996   377.8  740.13
   389.7  738.23   409.5  730.73  439.79730.2906     457  730.32  469.44734.2523
   488.7   734.6   500.6  732.64   524.4  723.57   532.3  722.85   540.2  724.08
  558.39728.3426   571.9  733.56   599.6  734.68   603.6  737.49  617.69754.2049
   643.2  775.15   702.6  805.35   722.4  812.01   742.2  831.08     762  846.63
#Mann= 9 ,-1 , 0
       0     .12       0  159.44    .016       0  222.73     .06       0
  439.79     .04       0  469.44     .12       0   524.4    .045       0
   540.2     .12       0  558.39    .016       0  617.69     .12       0
#XS Ineff= 2 , 0
          482.15  736.32
Permanent Ineff=
       F       F
Bank Sta=524.4,540.2
XS Rating Curve= 0 ,0
Exp/Cntr=0.3,0.1

Type RM Length L Ch R = 1 ,428.4   ,231.3,234.1,235.6
XS GIS Cut Line= 4
     1797177.727       408724.59     1796804.029      408995.423
     1796764.967      409262.351     1796796.217      409453.757
#Sta/Elev= 30
       0  833.84    15.9  822.19    59.7   799.4    83.6  791.75   135.3  770.02
  166.27744.7927   175.1  740.06  208.04 742.513  266.93739.6248  353.95737.9304
   367.6 737.508  390.42737.5361  471.91735.7649  495.37 733.741   548.8  732.84
   564.7  729.65   604.3  731.06     640  721.88     648  721.21   655.9  722.07
  704.33730.7007   747.1  737.46   751.1  740.08   766.9  758.46   774.8  764.31
   846.1  802.26   869.8  818.37   885.6  821.75   897.5   833.4   925.2  851.62
#Mann= 12 ,-1 , 0
       0     .12       0  166.27    .016       0  208.04     .12       0
  266.93     .06       0  353.95    .016       0   367.6     .06       0
  390.42     .12       0  471.91     .06       0  495.37    .016       0
     640    .045       0   655.9    .016       0  704.33     .12       0
Bank Sta=640,655.9
XS Rating Curve= 0 ,0
Exp/Cntr=0.3,0.1

Type RM Length L Ch R = 1 ,194.3   ,198.2,194.3,191.7
XS GIS Cut Line= 4
     1796968.092      408697.246     1796569.654      409021.465
     1796543.613      409271.465     1796655.592      409465.476
#Sta/Elev= 30
       0   742.5      12  738.56   23.06738.2991   61.14738.9468    67.7  739.21
    79.6  734.67   99.22 733.729   137.3 733.862   330.5  732.24   398.2  738.54
   478.7729.5167  480.01729.3955   513.7   726.5  521.18728.6919   533.6  733.43
  550.87733.9064   621.4  732.59   661.3  720.67   669.3  719.73   677.3  720.66
  699.35727.1805  729.05726.8514   753.1  726.62     769  730.28   800.4  729.81
   812.2  732.22   855.4  754.94   902.6  770.52   977.2  815.93     989  819.12
#Mann= 13 ,-1 , 0
       0     .12       0   23.06    .016       0   61.14     .12       0
   99.22    .016       0   137.3     .12       0   478.7    .016       0
  480.01     .12       0  521.18    .016       0  550.87     .12       0
   661.3    .045       0   677.3     .12       0  699.35    .016       0
  729.05     .12       0
#XS Ineff= 2 , 0
          592.36  735.27  705.88          728.38
Permanent Ineff=
       F       F
Bank Sta=661.3,677.3
XS Rating Curve= 0 ,0
Exp/Cntr=0.3,0.1

Chan Stop Cuts=-1
Use User Specified Reach Order=0
Composite Channel Slope=5